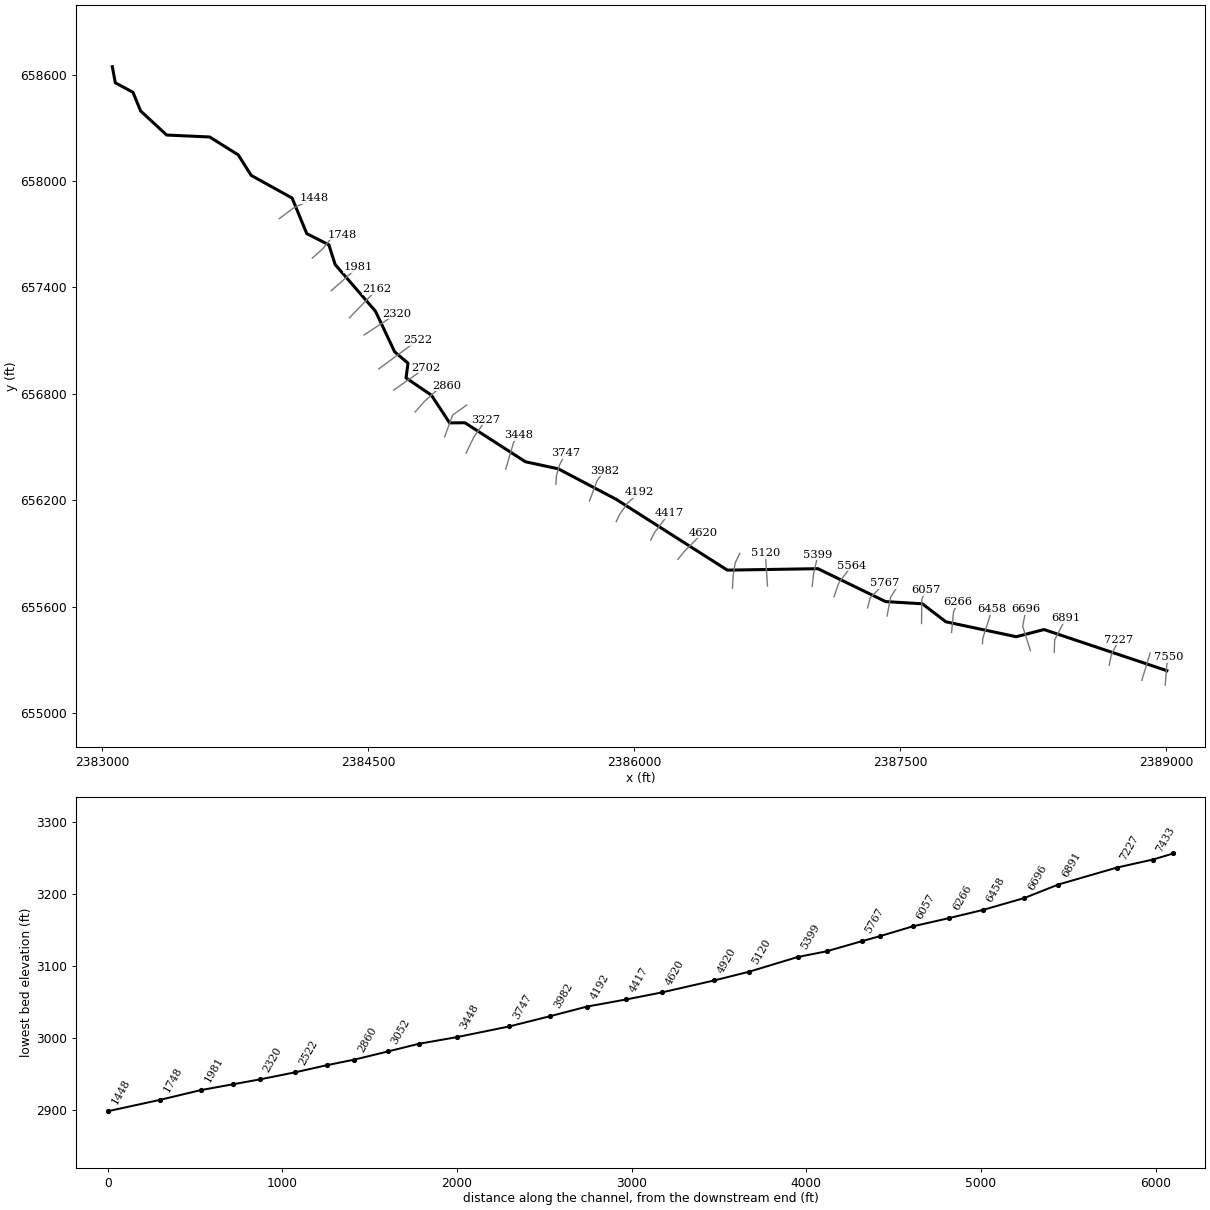
--- LOW2SPRRN.prj (project) ---

Proj Title=LOW2SPRRN
Current Plan=p01
Default Exp/Contr=0,0
English Units
Geom File=g01
Flow File=f01
Plan File=p01
BEGIN DESCRIPTION:
----------MODEL BY WOOD PLC 2022----------
AFH study
Randolph County, WV
HEC-RAS Version: RAS 6.2
Vertical Datum: NAVD88
Projection: NAD 1983 StatePlane West Virginia S FIPS 4702 (US Feet)
Terrain: 1-meter LIDAR (FEMA Region III 3DEP collected 2016-2018)
Land Use: 2019 NLCD
Hydrologic Method:
WV SIR2010-5033 regression equations
Additional Model Notes:
None
END DESCRIPTION:
DSS Export Rating Curves= 0
DSS Export Rating Curve Sorted= 0
DSS Export Volume Flow Curves= 0
DXF OffsetX= 0
DXF OffsetY= 0
DXF ScaleX= 0
DXF ScaleY= 0

--- LOW2SPRRN.p01 (plan) ---

Plan Title=Floodplain
Program Version=6.20
Short Identifier=Floodplain
Geom File=g01
Flow File=f01
Subcritical Flow
K Sum by GR= 0
Std Step Tol= 0.01
Critical Tol= 0.01
Num of Std Step Trials= 20
Max Error Tol= 0.3
Flow Tol Ratio= 0.001
Split Flow NTrial= 30
Split Flow Tol= 0.02
Split Flow Ratio= 0.02
Log Output Level= 0
Friction Slope Method= 1
Unsteady Friction Slope Method= 2
Unsteady Bridges Friction Slope Method= 1
Parabolic Critical Depth
Global Vel Dist= 0 , 0 , 0
Global Log Level= 0
CheckData=True
Encroach Param=-1 ,0,0, 0
Mapping Interval=1HOUR
Computation Time Step Use Courant=        0
Computation Time Step Use Time Series=    0
Computation Time Step Count To Double=0
Computation Time Step Max Doubling=0
Computation Time Step Max Halving=0
Computation Time Step Residence Courant=0
Run HTab= 0
Run UNet= 0
Run Sediment= 0
Run PostProcess= 0
Run WQNet= 0
Run RASMapper=-1
UNET Theta= 0
UNET Theta Warmup= 0
UNET ZTol= 0
UNET ZSATol= 0
UNET MxIter= 0
UNET Max Iter WO Improvement= 0
UNET MaxInSteps= 0
UNET DtIC= 0
UNET DtMin= 0
UNET MaxCRTS= 0
UNET WFStab= 0
UNET SFStab= 0
UNET WFX= 1
UNET SFX= 1
UNET Gravity=32.174
UNET 1D Methodology=Finite Difference
UNET DSS MLevel= 1
UNET Pardiso=0
UNET DZMax Abort= 0
UNET Use Existing IB Tables= 0
UNET Froude Reduction=False
UNET Froude Limit= 0
UNET Froude Power= 0
UNET D1 Cores= 0
UNET WindReference=Eulerian
UNET WindDragFormulation=Hsu (1988)
UNET D2 Coriolis=0
UNET D2 Cores= 0
UNET D2 Theta= 1
UNET D2 Theta Warmup= 1
UNET D2 Z Tol= 0.01
UNET D2 Volume Tol= 0.01
UNET D2 Max Iterations= 20
UNET D2 Equation= 0
UNET D2 RampUpFraction=0.1
UNET D2 TimeSlices= 1
UNET D2 Turbulence Formulation=Non-Conservative (original)
UNET D2 Eddy Viscosity=0.3
UNET D2 Transverse Eddy Viscosity=0.1
UNET D2 Smagorinsky Mixing=0
UNET D2 BCVolumeCheck=0
UNET D2 Cores=0
UNET D2 SolverType=PARDISO (Direct)
UNET D2 Minimum Iterations= 2147483647
UNET D2 Maximum Iterations= 2147483647
UNET D2 Restart Number= 10
UNET D2 Relaxation Coeff=1.3
UNET D2 SOR Precondition Iterations= 10
UNET D2 ILUT Maximum Fill= 8
UNET D2 ILUT Tolerance=1E-08
UNET D1D2 MaxIter= 0
UNET D1D2 ZTol=0.01
UNET D1D2 QTol=0.1
UNET D1D2 MinQTol=1
Write IC File= 0
Write IC File at Fixed DateTime=0
Write IC File at Sim End=0
Echo Input=False
Echo Parameters=False
Echo Output=False
Write Detailed= 0
HDF Write Warmup=0
HDF Write Time Slices=0
HDF Flush=0
HDF Compression= 1
HDF Chunk Size= 1
HDF Spatial Parts= 1
HDF Use Max Rows=0
HDF Fixed Rows= 1
Calibration Method= 0
Calibration Iterations= 20
Calibration Max Change=0.05
Calibration Tolerance=0.2
Calibration Maximum=1.5
Calibration Minimum=0.5
Calibration Optimization Method= 1
WQ AD Non Conservative
WQ ULTIMATE=-1
WQ Max Comp Step=1HOUR
WQ Output Interval=15MIN
WQ Output Selected Increments= 0
WQ Output face flow=0
WQ Output face velocity=0
WQ Output face area=0
WQ Output face dispersion=0
WQ Output cell volume=0
WQ Output cell surface area=0
WQ Output cell continuity=0
WQ Output cumulative cell continuity=0
WQ Output face conc=0
WQ Output face dconc_dx=0
WQ Output face courant=0
WQ Output face peclet=0
WQ Output face adv mass=0
WQ Output face disp mass=0
WQ Output cell mass=0
WQ Output cell source sink temp=0
WQ Output nsm pathways=0
WQ Output nsm derived pathways=0
WQ Create Restart=0
WQ Fixed Restart=0
WQ System Summary=0
WQ Write To DSS=0
Sorting and Armoring Iterations= 10
XS Update Threshold= 0.02
Bed Roughness Predictor= 0
Hydraulics Update Threshold= 0.02
Energy Slope Method= 1
Volume Change Method= 1
Sediment Retention Method= 0
Sediment TS Multiplier= 1
Warm Up Method= 0
XS Weighting Method= 0
Number of US Weighted Cross Sections= 1
Number of DS Weighted Cross Sections= 1
Upstream XS Weight=0
Main XS Weight=1
Downstream XS Weight=0
Number of DS XS's Weighted with US Boundary= 1
Upstream Boundary Weight= 1
Weight of XSs Associated with US Boundary= 0
Number of US XS's Weighted with DS Boundary= 1
Downstream Boundary Weight= 0.5
Weight of XSs Associated with DS Boundary= 0.5
Percentile Method= 0
Sediment Output Level= 3
Mass or Volume Output= 0
Output Increment Type= 1
Profile and TS Output Increment= 1
Transport Output Increment 1
XS Output Flag= 0
XS Output Increment= 10
Read HDF5 Sediment Hotstart= 0
Sediment Hotstart Type= 0
Write Gradation File= 0
Read Gradation Hotstart= 0
Write HDF5 File= 1
Write Binary Output= 1
Write DSS Sediment File= 0
DSS Sediment Output Type= 1
SV Curve= 0
Specific Gage Flag= 0
Subcell Erosion Methods= 0
Subcell Deposition Methods= 0
Advection Scheme= 1
Matrix Solver= 0
Implicit Weighting Factor= 1
Maximum Outer Loop Convergence Iterations= 5
Convergence Maximum Absolute= 0.001
Convergence RMSE= 0.0001
Grain Fractions Max Abs Error= 0.001
Max Subgrid Regions= 1
Max Subgrid Length Scale= 3.402823E+38
Initial Layer Thickness= 3.402823E+38
Min Layer Thickness= 3.402823E+38
Max Layer Thickness= 3.402823E+38
Number of Layers= 5

--- LOW2SPRRN.f01 (steady flow) ---

Flow Title=Flow
Program Version=6.20
Number of Profiles= 1
Profile Names=P100yr
River Rch & RM=LOW2SPRRN,Main,7550
     355
River Rch & RM=LOW2SPRRN,Main,5120
     395
River Rch & RM=LOW2SPRRN,Main,3982
     446
Boundary for River Rch & Prof#=LOW2SPRRN,Main            , 1
Up Type= 0
Dn Type= 3
Dn Slope=0.06605
DSS Import GetInterval= 0
DSS Import GetPeak= 0
DSS Import FillOption= 0

--- LOW2SPRRN.g01 (geometry) ---

Geom Title=Geometry
Program Version=6.20

River Reach=LOW2SPRRN       ,Main
Reach XY= 30
2389005.13604885655237.995586531 2388311.7362629655470.052648634
2388155.47444553655429.4721705652387758.31124615655513.755292079
2387625.33817667655615.4252358412387418.51200001655627.662000015
2387036.26700003655813.4060000182386525.41600002655805.160000011
2385897.17921752656205.3982519962385571.42299998656376.774000004
2385386.09300001656416.7049999982385044.51399998656636.756999999
2384958.57599999656635.8890000132384855.71099998656792.139000013
2384712.48200001656889.7950000022384723.76700002656972.694000006
2384648.24600001657036.9300000072384540.60699999657265.229000017
2384312.74300005657529.1180000012384277.15200001657640.663000003
2384152.58600003657703.5970000182384069.68700004657904.552000016
2383839.11957928658032.1348345172383765.78100003658147.955000013
2383604.84300001658248.9969999942383362.13500001658259.934000015
2383215.22264864658395.5945257712383172.03100002658501.079999998
2383072.33338303658554.6970697952383055.46232201658645.678342626

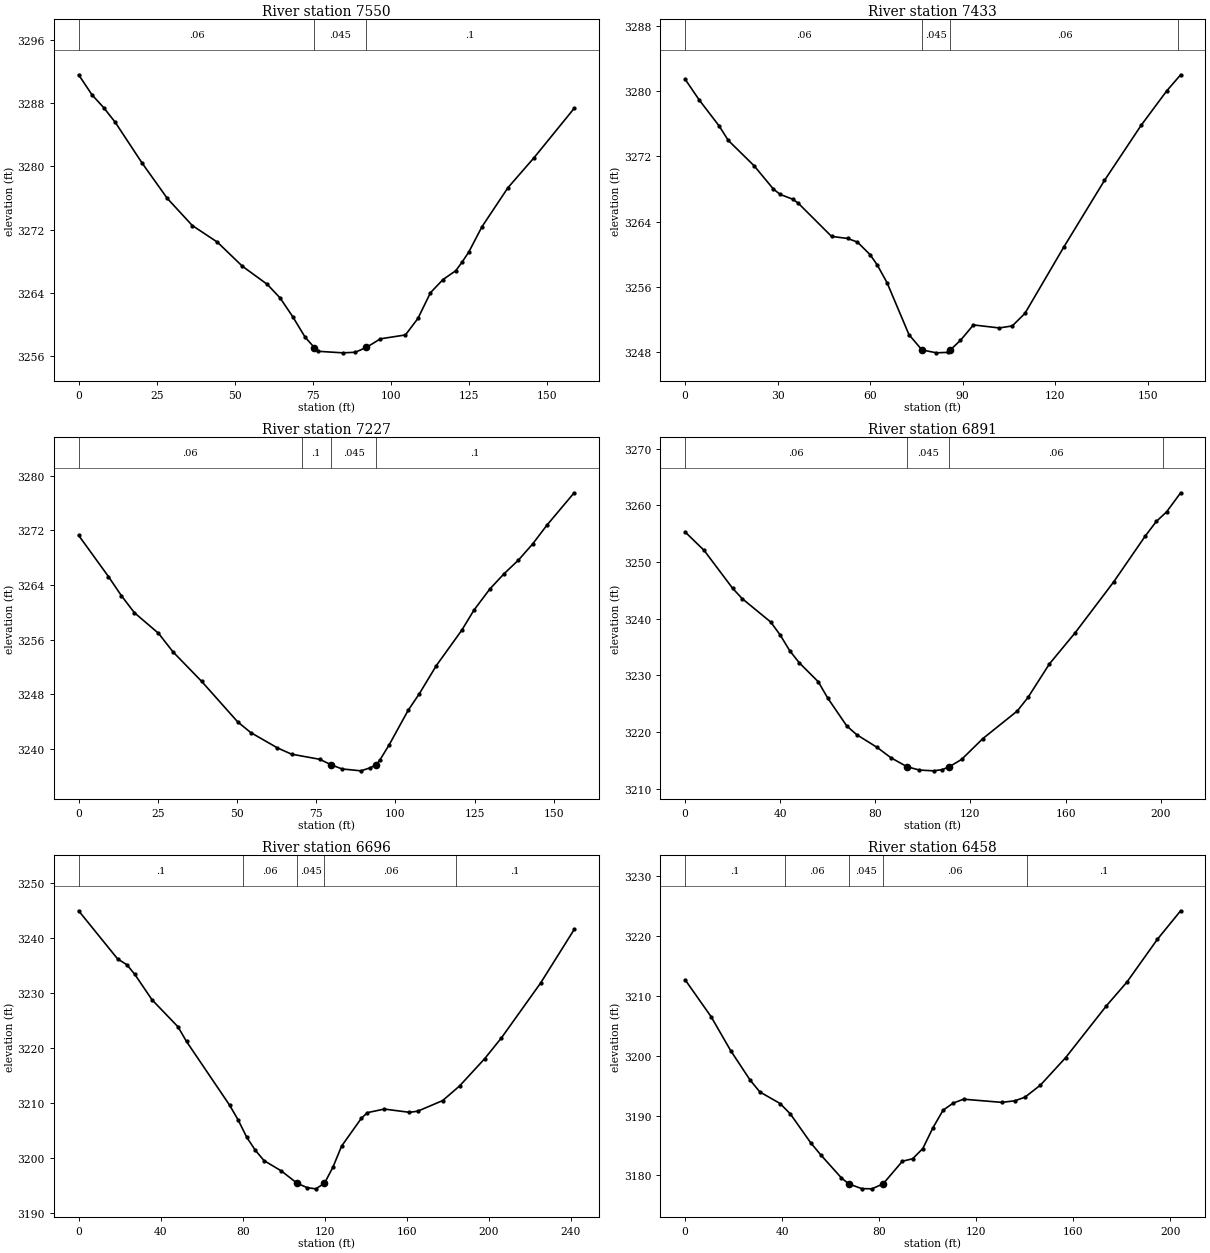
Type RM Length L Ch R = 1 ,7550    ,118.2,117.1,115.4
XS GIS Cut Line= 3
 2388995.8962898655156.9100314172389004.93296004655274.386744473
2389016.47981645655313.545648825
#Sta/Elev= 30
       0 3291.55     4.3 3289.01       8 3287.41    11.7 3285.56    20.3 3280.41
    28.4 3275.93    36.4 3272.51    44.4 3270.42    52.4 3267.38    60.4 3265.08
    64.5 3263.36    68.5 3261.02    72.5 3258.41   75.433257.113    76.5 3256.64
    84.5 3256.44    88.5 3256.51   92.063257.116    96.6 3258.21   104.6  3258.7
   108.6 3260.79   112.6 3264.03   116.6 3265.69   120.7 3266.81   122.7 3267.88
   124.9 3269.19   129.1 3272.37   137.4 3277.29   145.8  3281.1   158.6 3287.31
#Mann= 3, -1 ,  0
       0    0.06       0   75.43   0.045       0   92.06     0.1       0
Bank Sta=75.43,92.06
XS Rating Curve= 0 ,0
Exp/Cntr(USF)=0,0
Exp/Cntr=0.3,0.1

Type RM Length L Ch R = 1 ,7433    ,206.5,205.9,204.7
XS GIS Cut Line= 2
2388863.80648469655183.7625696962388910.80772846655337.432695857
#Sta/Elev= 30
       0 3281.47     4.6 3278.91      11 3275.76      14 3273.97    22.4 3270.85
    28.6 3268.02    30.8 3267.35    34.9 3266.76    36.7 3266.27    47.5  3262.2
    52.7 3261.95    55.9  3261.5      60 3259.96    62.3 3258.71    65.5 3256.52
    72.6 3250.16    76.8 3248.29    81.5 3247.93    85.1 3247.99   86.01 3248.29
    89.3 3249.46    93.5 3251.35   101.9 3250.98   106.1 3251.23   110.2 3252.76
   122.8 3260.89     136 3269.06   147.9 3275.82   156.2 3280.04   160.7 3282.01
#Mann= 4, -1 ,  0
       0    0.06       0    76.8   0.045       0   86.01    0.06       0
     160     0.1       0
Bank Sta=76.8,86.01
XS Rating Curve= 0 ,0
Exp/Cntr(USF)=0,0
Exp/Cntr=0.3,0.1

Type RM Length L Ch R = 1 ,7227    ,334.8,335.7,334.7
XS GIS Cut Line= 3
2388679.72040316655267.9384167062388691.66172522655327.100654178
2388734.83692746 655412.94902141
#Sta/Elev= 30
       0 3271.26     9.4 3265.23    13.5 3262.42    17.6 3259.93    25.2 3256.92
    29.8 3254.19    38.8 3249.89    50.2 3243.95    54.3 3242.39    62.7 3240.15
    67.2 3239.22    76.1 3238.47   79.573237.694    83.1 3237.06    89.1 3236.78
    92.1 3237.24   93.983237.695    95.1 3238.38      98 3240.58     104 3245.64
   107.5 3248.05   112.9 3252.19   120.9 3257.35   124.8 3260.33   129.8 3263.41
   134.3 3265.65   138.8 3267.63   143.3    3270   147.8 3272.75   156.4 3277.49
#Mann= 4, -1 ,  0
       0    0.06       0   70.36     0.1       0   79.57   0.045       0
   93.98     0.1       0
Bank Sta=79.57,93.98
XS Rating Curve= 0 ,0
Exp/Cntr(USF)=0,0
Exp/Cntr=0.3,0.1

Type RM Length L Ch R = 1 ,6891    ,188.5,194.9,200.4
XS GIS Cut Line= 3
2388369.73661322655341.1723632772388372.09809627655411.988061898
2388435.11667592655534.257277071
#Sta/Elev= 30
       0 3255.29       8 3252.04      20 3245.35      24 3243.54      36 3239.41
      40 3237.12      44 3234.35      48 3232.23      56 3228.88      60 3225.99
      68 3221.08    72.2 3219.54    80.7 3217.32    86.6 3215.47   93.313213.898
    98.5 3213.31   104.5 3213.17   108.2 3213.39  111.143213.898   116.3 3215.19
   125.2 3218.85   139.7 3223.72   144.2 3226.11   153.2 3232.02   163.9 3237.44
   180.2 3246.46   193.5 3254.56   198.2 3257.16   202.5 3258.83   208.4  3262.2
#Mann= 4, -1 ,  0
       0    0.06       0   93.31   0.045       0  111.14    0.06       0
  200.86     0.1       0
Bank Sta=93.31,111.14
XS Rating Curve= 0 ,0
Exp/Cntr(USF)=0,0
Exp/Cntr=0.3,0.1

Type RM Length L Ch R = 1 ,6696    ,240.1,238.5,231.6
XS GIS Cut Line= 3
2388235.32545568655351.043592159 2388191.5622082655488.386264597
2388210.07166079655584.050748783
#Sta/Elev= 30
       0 3245.03      19 3236.27    23.6 3235.18    27.4 3233.44    35.8 3228.81
    48.4 3223.91    52.6 3221.22    73.6 3209.62    77.8 3206.91      82 3203.75
    86.2 3201.38    90.4 3199.52    98.8 3197.65  106.533195.395   111.4  3194.6
   115.6 3194.38  119.863195.393     124 3198.34   128.2 3202.16   137.9 3207.26
   140.8 3208.26     149 3208.91   161.3 3208.32   165.3 3208.52   177.5 3210.46
   185.7 3213.11   197.9 3218.06   206.1 3221.86   225.2 3231.85   241.6 3241.62
#Mann= 5, -1 ,  0
       0     0.1       0      80    0.06       0  106.53   0.045       0
  119.86    0.06       0  184.15     0.1       0
Bank Sta=106.53,119.86
XS Rating Curve= 0 ,0
Exp/Cntr(USF)=0,0
Exp/Cntr=0.3,0.1

Type RM Length L Ch R = 1 ,6458    ,189.2,191.2,192
XS GIS Cut Line= 3
2387964.71575374655390.4580137642387966.57515091655421.447966559
2388019.87786972655586.314515429
#Sta/Elev= 30
       0 3212.72    10.7 3206.55    18.8 3200.85    26.8 3195.93    30.8 3193.95
    39.2    3192    43.4 3190.26    51.8 3185.43      56 3183.38    64.4 3179.58
   67.45 3178.56    72.8 3177.77      77 3177.73   81.633178.563    89.6 3182.35
    93.8 3182.76      98 3184.47   102.2 3187.97   106.4 3190.91   110.6 3192.09
   114.8 3192.73   130.6  3192.2   135.9 3192.46   140.1 3193.06   146.5 3195.09
   156.9 3199.69   173.7 3208.36   182.1  3212.3   194.7 3219.48   204.3 3224.26
#Mann= 5, -1 ,  0
       0     0.1       0   41.05    0.06       0   67.45   0.045       0
   81.63    0.06       0  141.05     0.1       0
Bank Sta=67.45,81.63
XS Rating Curve= 0 ,0
Exp/Cntr(USF)=0,0
Exp/Cntr=0.3,0.1

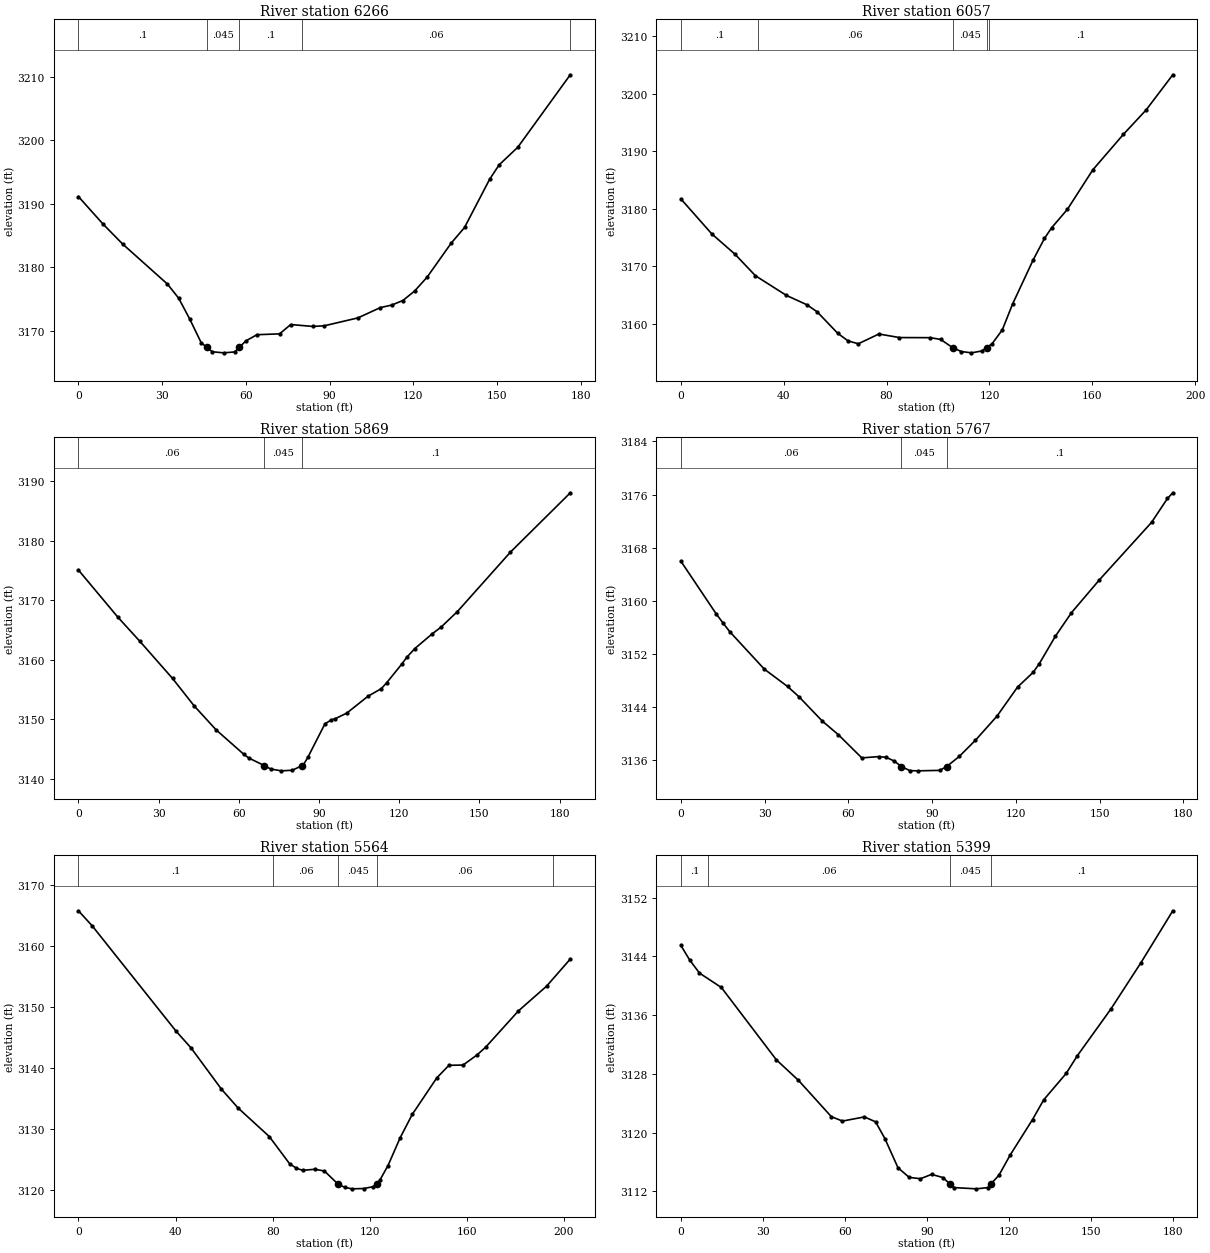
Type RM Length L Ch R = 1 ,6266    ,209.9,209.8,211.9
XS GIS Cut Line= 3
2387790.43850951655453.4178798972387801.54970707655571.090750524
2387827.58918668655623.071568475
#Sta/Elev= 30
       0 3191.15     8.7 3186.87    15.8 3183.69    31.9 3177.36    35.9 3175.15
    39.9 3171.84      44 3168.12   46.013167.391      48 3166.69      52 3166.52
      56 3166.66    57.73167.391      60  3168.4      64 3169.38    72.1 3169.51
    76.1 3170.98    84.1 3170.68    88.2 3170.79   100.2 3172.03   108.2 3173.65
   112.3 3174.05   116.3 3174.77   120.5 3176.26     125 3178.46   133.6  3183.8
   138.4 3186.28   147.4 3193.88   150.8 3196.15   157.5 3198.93   176.3 3210.35
#Mann= 5, -1 ,  0
       0     0.1       0   46.01   0.045       0    57.7     0.1       0
      80    0.06       0  176.33     0.1       0
Bank Sta=46.01,57.7
XS Rating Curve= 0 ,0
Exp/Cntr(USF)=0,0
Exp/Cntr=0.3,0.1

Type RM Length L Ch R = 1 ,6057    ,188.6,187.8,186.2
XS GIS Cut Line= 3
2387621.01200096655504.2269420742387622.27236788655640.327634329
2387644.94247027655690.703373103
#Sta/Elev= 30
       0  3181.7      12 3175.62      21 3172.09      29 3168.32      41 3164.91
      49 3163.27      53 3162.04      61  3158.3      65 3156.98      69 3156.48
      77 3158.18      85 3157.56      97 3157.54     101 3157.24  105.633155.821
     109 3155.13     113  3154.9     117 3155.22  118.873155.819     121 3156.47
     125  3158.9     129 3163.41     137 3171.08   141.4 3174.83   144.2 3176.69
   150.3 3179.88   160.2 3186.77   172.1 3192.95   180.9 3197.18   191.3 3203.32
#Mann= 5, -1 ,  0
       0     0.1       0      30    0.06       0  105.63   0.045       0
  118.87    0.06       0     120     0.1       0
Bank Sta=105.63,118.87
XS Rating Curve= 0 ,0
Exp/Cntr(USF)=0,0
Exp/Cntr=0.3,0.1

Type RM Length L Ch R = 1 ,5869    ,107,102,98.3
XS GIS Cut Line= 3
2387426.35917382655546.6086596742387446.74527525 655652.97153507
2387487.40855004655716.766630895
#Sta/Elev= 30
       0 3175.04    14.8 3167.09      23 3163.05    35.2 3156.82    43.3  3152.2
    51.5 3148.18    61.8 3144.09    63.7 3143.45   69.58 3142.16    71.9  3141.6
    75.9 3141.29      80 3141.39   83.593142.161    84.1 3142.27    85.8 3143.55
    92.2 3149.19    94.6 3149.85      96 3150.04   100.4    3151   108.3 3153.83
   113.3 3155.11   115.3  3156.1   121.1 3159.32   122.8 3160.37   125.8 3161.83
   132.3 3164.31   135.6 3165.43   141.7 3168.04   161.6 3178.06     184 3188.03
#Mann= 3, -1 ,  0
       0    0.06       0   69.58   0.045       0   83.59     0.1       0
Bank Sta=69.58,83.59
XS Rating Curve= 0 ,0
Exp/Cntr(USF)=0,0
Exp/Cntr=0.3,0.1

Type RM Length L Ch R = 1 ,5767    ,200.5,202.9,202.6
XS GIS Cut Line= 3
2387316.33793402655592.2210899472387330.87643039 655648.07952338
2387413.51630451655733.014949559
#Sta/Elev= 30
       0 3165.96    12.7    3158    15.2  3156.6    17.5 3155.35    29.9 3149.71
    38.2 3147.11    42.3 3145.56    50.6 3141.92    56.4 3139.85    64.8 3136.36
    71.1 3136.56    73.6 3136.43    76.4 3135.89   78.983135.062      82 3134.44
    84.9 3134.41    92.7 3134.48   95.223135.062    99.7 3136.57   105.5 3139.01
   113.2 3142.63   120.6 3147.02   126.2 3149.24   128.4 3150.55   134.1 3154.64
   139.9 3158.21   149.9 3163.15   168.6 3171.81   174.3 3175.41   176.2 3176.26
#Mann= 3, -1 ,  0
       0    0.06       0   78.98   0.045       0   95.22     0.1       0
Bank Sta=78.98,95.22
XS Rating Curve= 0 ,0
Exp/Cntr(USF)=0,0
Exp/Cntr=0.3,0.1

Type RM Length L Ch R = 1 ,5564    ,162.8,165.1,169.4
XS GIS Cut Line= 3
2387126.92104935655655.1559900422387155.64144153655735.846691725
2387226.33379992655828.991050652
#Sta/Elev= 30
       0 3165.77     5.7 3163.29    40.1 3146.12    46.4 3143.32    58.9 3136.58
    65.8 3133.48    78.6 3128.83      87 3124.36    89.8 3123.64    92.3  3123.3
    97.4 3123.47   101.3 3123.19     107 3121.01   109.8  3120.5   112.7 3120.27
   117.5 3120.32   121.2 3120.61  122.883121.012   124.1 3121.66   127.5 3124.08
   132.5 3128.62   137.5 3132.46   147.6 3138.43   152.6 3140.49   158.4 3140.52
   164.1 3142.16   167.7 3143.44   181.2 3149.38   192.8 3153.43   202.6 3157.88
#Mann= 5, -1 ,  0
       0     0.1       0      80    0.06       0     107   0.045       0
  122.88    0.06       0  195.65     0.1       0
Bank Sta=107,122.88
XS Rating Curve= 0 ,0
Exp/Cntr(USF)=0,0
Exp/Cntr=0.3,0.1

Type RM Length L Ch R = 1 ,5399    ,276.8,278.7,280.9
XS GIS Cut Line= 3
2387004.32339635655714.4367406282387011.46480577655782.171017094
2387036.11650145655891.201188936
#Sta/Elev= 30
       0 3145.49     3.2 3143.52     6.8 3141.73    14.8 3139.77    34.9 3129.92
      43 3127.12      55 3122.18    59.1 3121.57    67.1 3122.14    71.2 3121.47
    74.6 3119.19    79.4 3115.21    83.5  3113.9    87.6 3113.72    91.7 3114.31
    95.8 3113.88   98.27 3113.05    99.9 3112.51   108.1 3112.34   112.2 3112.51
  113.483113.052   116.3 3114.18   120.4 3116.93   128.6 3121.78   132.7 3124.47
   140.9 3128.06     145 3130.48   157.3 3136.86   168.2 3143.12   179.9 3150.22
#Mann= 4, -1 ,  0
       0     0.1       0      10    0.06       0   98.27   0.045       0
  113.48     0.1       0
Bank Sta=98.27,113.48
XS Rating Curve= 0 ,0
Exp/Cntr(USF)=0,0
Exp/Cntr=0.3,0.1

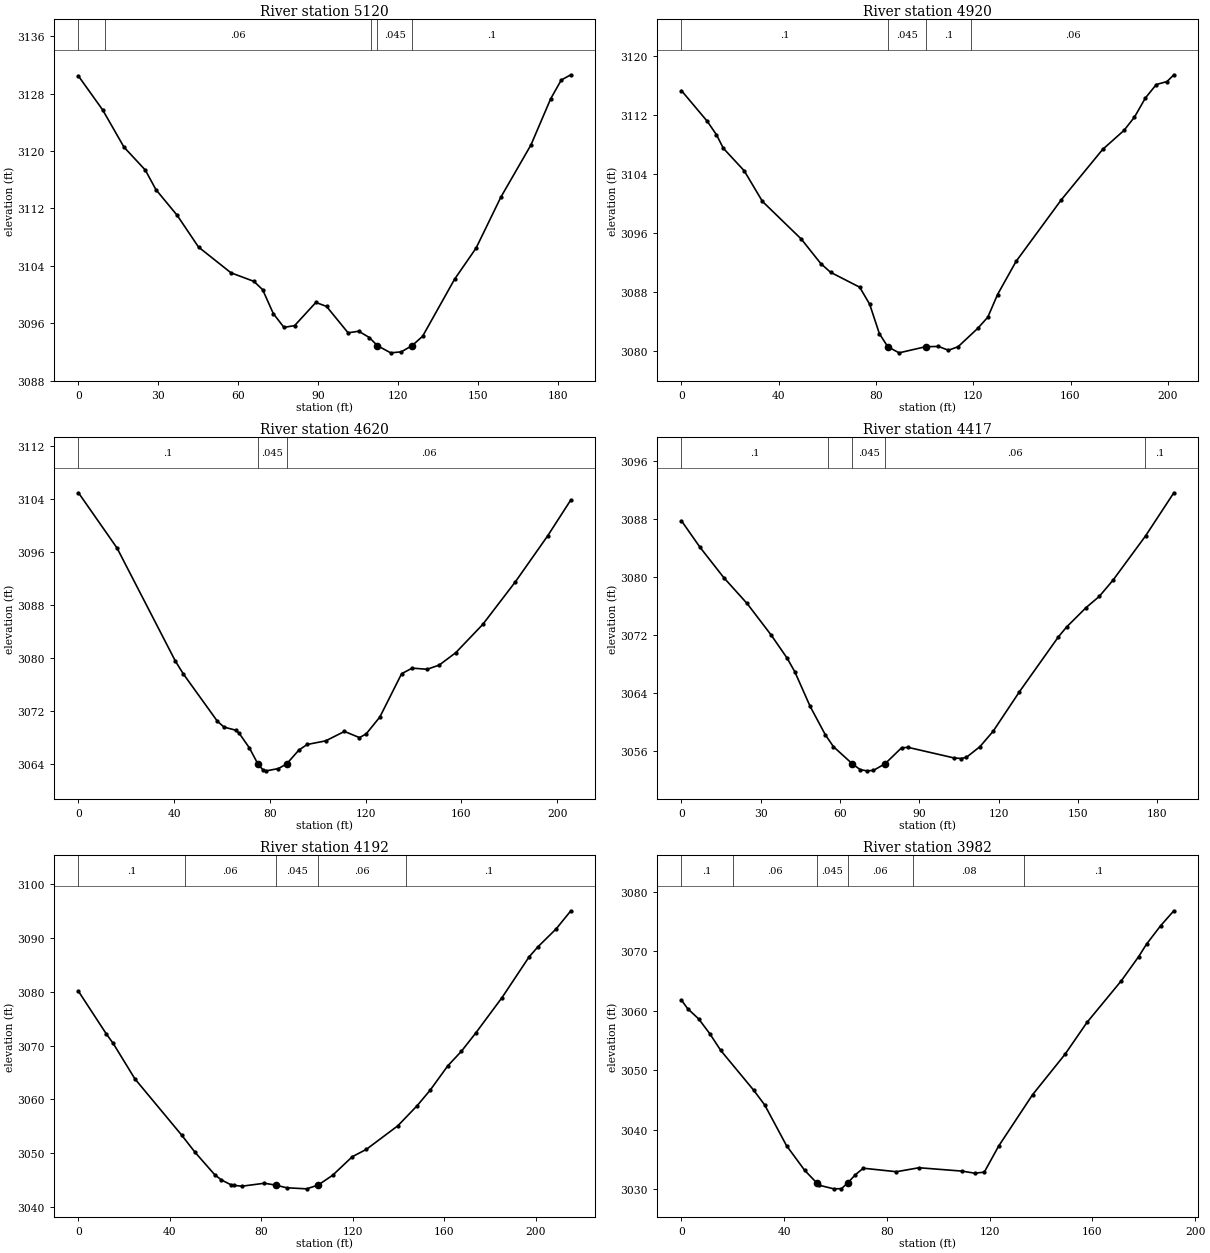
Type RM Length L Ch R = 1 ,5120    ,200.1,199.8,196.2
XS GIS Cut Line= 2
2386751.73339873655716.1365515152386739.76578336655900.771480238
#Sta/Elev= 30
       0 3130.43     9.1 3125.71    17.1 3120.53    25.1 3117.34    29.1 3114.61
    37.1 3111.02    45.1 3106.61    57.3 3103.02    65.9 3101.83    69.2 3100.67
    73.2 3097.34    77.2 3095.42    81.2 3095.66    89.2 3098.89    93.2 3098.34
   101.3 3094.66   105.3 3094.88   109.3    3094  112.293092.879   117.3 3091.87
   121.3 3092.01  125.363092.877   129.3 3094.18   141.3 3102.12   149.4 3106.47
   158.7 3113.56     170 3120.83   177.4 3127.25   181.4 3129.88     185 3130.61
#Mann= 5, -1 ,  0
       0     0.1       0      10    0.06       0     110     0.1       0
  112.29   0.045       0  125.36     0.1       0
Bank Sta=112.29,125.36
XS Rating Curve= 0 ,0
Exp/Cntr(USF)=0,0
Exp/Cntr=0.3,0.1

Type RM Length L Ch R = 1 ,4920    ,304.2,300.4,295.6
XS GIS Cut Line= 4
2386554.18412202655703.9939054862386558.08885607655773.163480125
2386569.24523908655844.5643313642386595.15736639655899.732963824
#Sta/Elev= 30
       0 3115.32    10.6 3111.16    14.4 3109.33    17.2  3107.5    25.8 3104.44
    33.3 3100.28    49.3 3095.16    57.3 3091.84    61.3 3090.66    73.3 3088.63
    77.4 3086.32    81.4 3082.32   84.863080.542    89.5 3079.72   100.4 3080.55
   105.7 3080.59   109.8 3080.07   113.8 3080.56   121.9 3083.06     126 3084.57
     130 3087.64   137.6 3092.13   156.2 3100.49   173.2 3107.33     182 3109.92
   186.3 3111.72   190.8 3114.32   195.3 3116.15   199.7 3116.55   202.5 3117.47
#Mann= 4, -1 ,  0
       0     0.1       0   84.86   0.045       0   100.4     0.1       0
  119.28    0.06       0
Bank Sta=84.86,100.4
XS Rating Curve= 0 ,0
Exp/Cntr(USF)=0,0
Exp/Cntr=0.3,0.1

Type RM Length L Ch R = 1 ,4620    ,202.3,203.2,203.8
XS GIS Cut Line= 3
2386246.08270376 655865.68049707 2386280.7676099655908.705949367
2386387.02290679656015.243416565
#Sta/Elev= 30
       0 3104.93    16.1 3096.61    40.5 3079.55    43.8 3077.63      58 3070.51
    60.8 3069.61    65.8 3069.14    67.2 3068.65    71.4 3066.48   74.963064.056
    77.1 3063.15    78.5 3063.02    83.5 3063.36   86.963064.056      92 3066.12
    95.5 3066.99   103.3 3067.54   111.1 3068.96   117.4 3068.03   120.2 3068.59
   125.9 3071.13     135 3077.66   139.4  3078.5   145.7 3078.33   150.7 3078.96
   157.6 3080.82   168.9 3085.09   182.5  3091.5     196 3098.43   205.7 3103.86
#Mann= 3, -1 ,  0
       0     0.1       0   74.96   0.045       0   86.96    0.06       0
Bank Sta=74.96,86.96
XS Rating Curve= 0 ,0
Exp/Cntr(USF)=0,0
Exp/Cntr=0.3,0.1

Type RM Length L Ch R = 1 ,4417    ,224.4,225,224.5
XS GIS Cut Line= 3
2386093.28466755655974.7487328392386113.25794815656015.617711493
2386198.66177754656127.579063689
#Sta/Elev= 30
       0 3087.75       7 3084.11    16.1 3079.88    24.8 3076.37    33.9 3072.03
    39.9 3068.87    42.9 3066.94    48.7 3062.17    54.4 3058.29    57.5 3056.63
   64.593054.285    67.6 3053.47    70.1  3053.3    72.6 3053.35   77.063054.285
    83.3 3056.48    85.8 3056.53   103.1 3055.08   105.8    3055   107.8 3055.16
   112.9 3056.62   117.9 3058.74   127.9 3064.21   142.6 3071.75   145.7 3073.11
   153.1 3075.79   158.1 3077.34   163.2 3079.53   175.6 3085.67   186.3 3091.61
#Mann= 5, -1 ,  0
       0     0.1       0   55.49    0.06       0   64.59   0.045       0
   77.06    0.06       0  175.49     0.1       0
Bank Sta=64.59,77.06
XS Rating Curve= 0 ,0
Exp/Cntr(USF)=0,0
Exp/Cntr=0.3,0.1

Type RM Length L Ch R = 1 ,4192    ,206.9,209.9,211.4
XS GIS Cut Line= 4
2385898.08772995656078.9281700572385918.26425116656120.795456909
2385962.73827675 656183.356137172386030.79762252 656245.46716871
#Sta/Elev= 30
       0 3080.09    12.2 3072.15    15.2 3070.39    24.7  3063.8    45.2 3053.32
      51 3050.15    59.6 3045.99    62.5 3045.02    66.6 3044.14    68.2    3044
    71.5 3043.85    81.3  3044.4    86.2 3044.06    91.1 3043.56    99.8 3043.36
  104.853044.062   111.2 3045.89   119.8 3049.34   125.9 3050.69   139.7 3055.08
   148.2 3058.84   153.9 3061.73   161.5  3066.2   167.5 3068.93   173.7 3072.28
   185.3 3078.93   197.1 3086.47     201 3088.36     209 3091.71   215.4 3095.06
#Mann= 5, -1 ,  0
       0     0.1       0   46.48    0.06       0    86.2   0.045       0
  104.85    0.06       0  143.23     0.1       0
Bank Sta=86.2,104.85
XS Rating Curve= 0 ,0
Exp/Cntr(USF)=0,0
Exp/Cntr=0.3,0.1

Type RM Length L Ch R = 1 ,3982    ,234.1,234.9,234.8
XS GIS Cut Line= 3
2385747.25430392656194.9008907642385790.80098526656310.410254634
2385830.75650429656365.745568559
#Sta/Elev= 30
       0 3061.82     2.4 3060.39     6.7 3058.66      11 3056.19    15.3 3053.35
    28.1 3046.67    32.4 3044.19    40.9 3037.34      48 3033.17   52.593031.107
    53.7 3030.67    59.3 3030.07    62.3  3030.1   64.823031.107    67.7 3032.44
    70.8 3033.54    83.7 3032.95    92.5 3033.62   109.3 3033.05   114.2  3032.7
   117.9 3032.88   123.5 3037.27   136.7 3045.91   149.3 3052.69   157.9 3058.08
   171.3  3065.1     178 3069.14   181.1 3071.26   186.6 3074.36   191.7 3076.85
#Mann= 6, -1 ,  0
       0     0.1       0      20    0.06       0   52.59   0.045       0
   64.82    0.06       0      90    0.08       0  133.45     0.1       0
Bank Sta=52.59,64.82
XS Rating Curve= 0 ,0
Exp/Cntr(USF)=0,0
Exp/Cntr=0.3,0.1

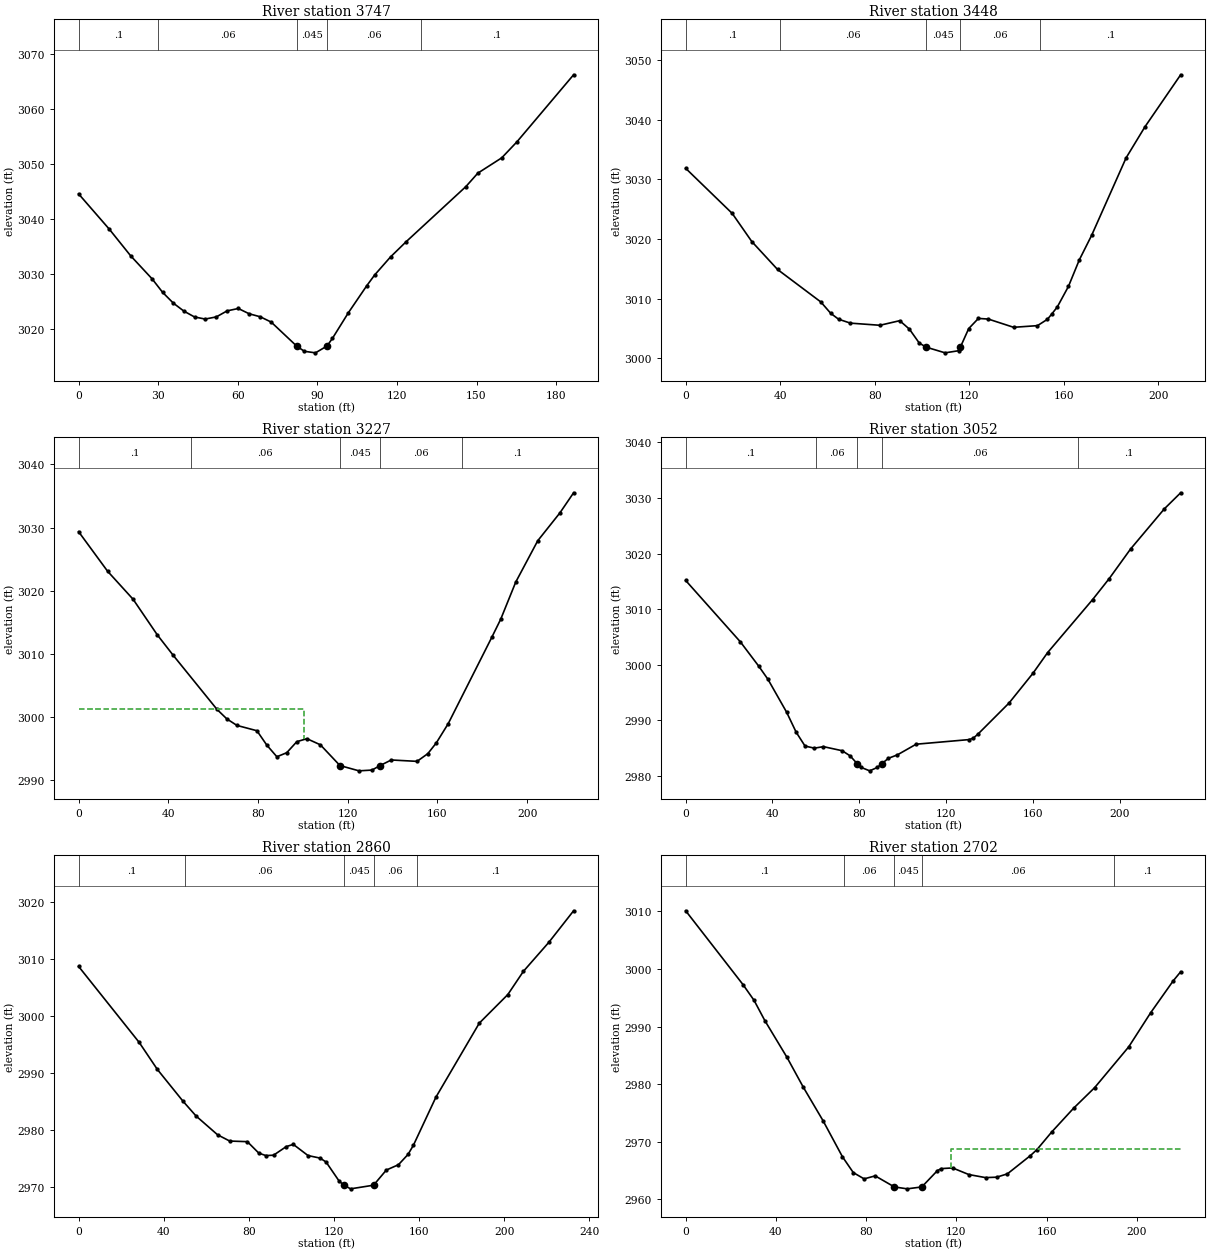
Type RM Length L Ch R = 1 ,3747    ,298.1,298.9,298.5
XS GIS Cut Line= 4
2385558.11887124656289.568716832 2385560.8679315656336.460408953
2385577.60250601656396.147058036 2385612.8403562656465.375599377
#Sta/Elev= 30
       0 3044.64    11.6 3038.21    19.6  3033.4    27.7  3029.2    31.7 3026.73
    35.7 3024.79    39.7 3023.33    43.7 3022.27    47.7 3021.89    51.9 3022.28
      56 3023.38    60.2 3023.81    64.3 3022.85    68.5  3022.3    72.6 3021.34
   82.193016.986    85.1 3016.03    89.3 3015.75   93.64 3016.99    95.7 3018.39
   101.7 3023.04   108.6 3027.93   111.6  3029.9   117.6 3033.19   123.5 3035.96
     146 3045.97   150.5 3048.41   159.5 3051.19   165.2 3054.08   186.6 3066.29
#Mann= 5, -1 ,  0
       0     0.1       0      30    0.06       0   82.19   0.045       0
   93.64    0.06       0  128.96     0.1       0
Bank Sta=82.19,93.64
XS Rating Curve= 0 ,0
Exp/Cntr(USF)=0,0
Exp/Cntr=0.3,0.1

Type RM Length L Ch R = 1 ,3448    ,223.7,220.6,218.4
XS GIS Cut Line= 3
2385274.78141844656374.2745583442385319.44380325656526.286265803
2385348.84451841656567.987010244
#Sta/Elev= 30
       0 3031.86    19.7  3024.3      28 3019.58    38.9  3014.9    57.2 3009.46
    61.4 3007.55    64.7 3006.57    69.7 3005.91    82.2 3005.55    90.6 3006.32
    94.7  3004.9    98.9 3002.55  101.923001.866   109.8 3000.93   115.6 3001.29
  116.243001.865   119.8    3005   123.9  3006.7   128.1 3006.59   138.8 3005.21
   148.9 3005.49   153.1 3006.55   154.9 3007.41   157.3 3008.63     162 3012.06
   166.6 3016.51   171.8 3020.61   186.4 3033.61   194.4 3038.83   209.5 3047.54
#Mann= 5, -1 ,  0
       0     0.1       0      40    0.06       0  101.92   0.045       0
  116.24    0.06       0     150     0.1       0
Bank Sta=101.92,116.24
XS Rating Curve= 0 ,0
Exp/Cntr(USF)=0,0
Exp/Cntr=0.3,0.1

Type RM Length L Ch R = 1 ,3227    ,172.4,175.3,176.9
XS GIS Cut Line= 3
2385051.38047261656465.5874777272385095.20050483 656556.40849992
2385164.50182652656654.181636705
#Sta/Elev= 30
       0 3029.36    12.9 3023.11    24.3 3018.66    35.1 3013.02    42.2 3009.78
    61.7 3001.23    66.1 2999.72    70.6 2998.69    79.5 2997.85    83.9 2995.58
    88.4 2993.73    92.8 2994.37    97.3 2996.12   101.8 2996.59   107.8 2995.62
  116.532992.335     125  2991.5   130.8 2991.62  134.412992.335   139.4 2993.22
   150.9    2993   155.7 2994.22   159.5 2995.93   164.8 2998.97   184.2 3012.62
   188.2  3015.5   194.9 3021.38   204.7 3027.92   214.6 3032.34   220.7 3035.52
#Mann= 5, -1 ,  0
       0     0.1       0      50    0.06       0  116.53   0.045       0
  134.41    0.06       0  170.84     0.1       0
#XS Ineff= 2 , 0
          100.62 3001.24
Permanent Ineff=
       F       F
Bank Sta=116.53,134.41
XS Rating Curve= 0 ,0
Exp/Cntr(USF)=0,0
Exp/Cntr=0.3,0.1

Type RM Length L Ch R = 1 ,3052    ,192.9,191.8,187.8
XS GIS Cut Line= 3
 2384930.4224955656557.5781805092384975.60584667656680.075265917
2385054.92772984656736.805473504
#Sta/Elev= 30
       0 3015.18    25.2 3004.14    33.7 2999.75    37.9 2997.41    46.5  2991.5
    50.9  2987.9      55  2985.4    59.3 2985.02    63.5 2985.29    72.1 2984.56
    75.8 2983.63   79.042982.224    80.6  2981.6    84.8 2980.94    88.3 2981.55
   90.392982.224    93.4 2983.19    97.6 2983.82   106.2 2985.73   130.6 2986.56
   132.5 2986.81   134.6 2987.51     149 2993.13     160 2998.47   166.8 3002.21
   187.5 3011.73   195.2 3015.53     205 3020.83   220.6 3028.07   228.1 3030.95
#Mann= 5, -1 ,  0
       0     0.1       0      60    0.06       0   79.04   0.045       0
   90.39    0.06       0  180.56     0.1       0
Bank Sta=79.04,90.39
XS Rating Curve= 0 ,0
Exp/Cntr(USF)=0,0
Exp/Cntr=0.3,0.1

Type RM Length L Ch R = 1 ,2860    ,157.8,158,156.8
XS GIS Cut Line= 4
2384763.65585114656697.4809608382384815.97610183656756.748435241
 2384881.9103254656816.3235204952384939.82894202656845.168406273
#Sta/Elev= 30
       0  3008.7    28.5 2995.33      37  2990.6    49.1 2984.99    55.2 2982.41
    65.3 2979.11      71 2978.01    79.3  2977.9    84.7 2975.88      88 2975.46
    91.6 2975.52    97.6 2977.04   100.9 2977.42   107.8 2975.46   113.5 2975.01
   116.3 2974.32   122.5 2970.93   124.8 2970.24   127.8 2969.61   138.6 2970.25
   144.6 2972.91   150.3 2973.85   154.8 2975.66   157.3 2977.25   167.9 2985.72
   188.3 2998.74   201.7 3003.76     209 3007.83     221 3012.95   232.6 3018.48
#Mann= 5, -1 ,  0
       0     0.1       0      50    0.06       0   124.8   0.045       0
   138.6    0.06       0  159.06     0.1       0
Bank Sta=124.8,138.6
XS Rating Curve= 0 ,0
Exp/Cntr(USF)=0,0
Exp/Cntr=0.3,0.1

Type RM Length L Ch R = 1 ,2702    ,178.6,180.4,178.9
XS GIS Cut Line= 2
2384643.36966607656821.1439441972384823.00785813656947.043254109
#Sta/Elev= 30
       0  3010.1    25.4 2997.29    30.3 2994.56    35.1 2991.03    44.9 2984.66
    52.1  2979.5    60.9 2973.65    69.5 2967.39    74.3 2964.65    79.1 2963.56
      84 2964.08    92.5 2962.16    98.2 2961.83  104.66 2962.16   111.6    2965
   113.3 2965.34   118.3 2965.46   125.5 2964.31   132.9 2963.78   137.8 2963.85
   142.6 2964.43   152.8  2967.6   155.7 2968.64   162.2 2971.68   171.9 2975.81
   181.3 2979.41   196.4 2986.49   206.1  2992.4   216.1 2997.94   219.4 2999.51
#Mann= 5, -1 ,  0
       0     0.1       0      70    0.06       0    92.5   0.045       0
  104.66    0.06       0     190     0.1       0
#XS Ineff= 2 , 0
                          117.48         2968.73
Permanent Ineff=
       F       F
Bank Sta=92.5,104.66
XS Rating Curve= 0 ,0
Exp/Cntr(USF)=0,0
Exp/Cntr=0.3,0.1

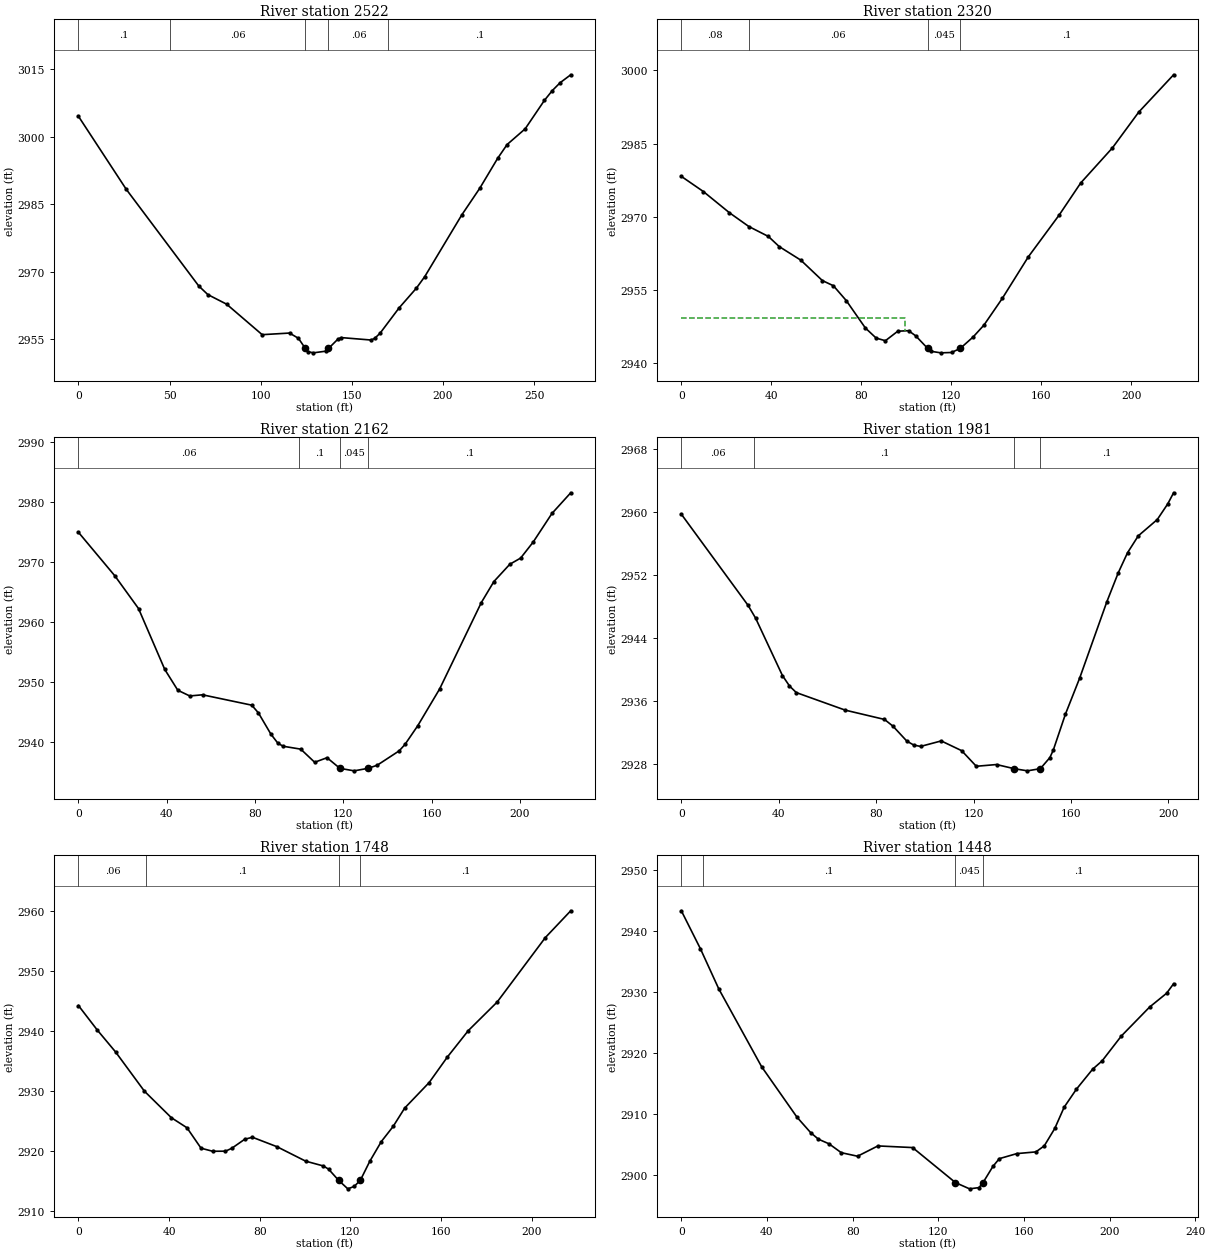
Type RM Length L Ch R = 1 ,2522    ,201.8,201.9,201.5
XS GIS Cut Line= 2
2384559.10267628656940.554562969 2384776.2881851657101.181519193
#Sta/Elev= 30
       0 3004.58    26.2 2988.36      66 2966.85      71 2964.93    81.3  2962.8
   100.8 2956.02   115.8 2956.38   120.7 2955.21   124.52952.946   125.7 2952.25
   128.9 2951.98   135.7 2952.35  137.182952.947   142.3 2955.01   144.2 2955.37
   160.5 2954.83   162.5 2955.18   165.5 2956.35   175.9 2961.96   185.4 2966.36
     190 2968.93   210.3 2982.64   220.2 2988.59     230 2995.24   235.2 2998.31
   245.1  3001.8   255.7 3008.15     260 3010.31   264.3 3012.06   270.1 3013.82
#Mann= 5, -1 ,  0
       0     0.1       0      50    0.06       0   124.5   0.045       0
  137.18    0.06       0     170     0.1       0
Bank Sta=124.5,137.18
XS Rating Curve= 0 ,0
Exp/Cntr(USF)=0,0
Exp/Cntr=0.3,0.1

Type RM Length L Ch R = 1 ,2320    ,155.7,157.6,158.7
XS GIS Cut Line= 2
2384475.79228099 657131.985110892384658.69127165657252.132265859
#Sta/Elev= 30
       0 2978.28     9.8 2975.17    21.4 2970.82      30 2968.01    38.7 2965.97
    43.5  2963.9    53.1 2961.12    62.7 2956.93    67.6 2955.87    73.3 2952.84
    81.8 2947.22    86.6 2945.15    90.7 2944.61    96.2 2946.56     101 2946.67
   104.2  2945.6  109.482943.044   110.9 2942.45   115.3 2942.13   120.1  2942.2
  123.992943.044   129.7 2945.38   134.5 2947.81   142.7 2953.31   154.2 2961.78
     168  2970.4   177.5 2976.92   191.6 2984.11   203.3 2991.44   218.8 2999.09
#Mann= 4, -1 ,  0
       0    0.08       0      30    0.06       0  109.48   0.045       0
  123.99     0.1       0
#XS Ineff= 2 , 0
           99.49  2949.2
Permanent Ineff=
       F       F
Bank Sta=109.48,123.99
XS Rating Curve= 0 ,0
Exp/Cntr(USF)=0,0
Exp/Cntr=0.3,0.1

Type RM Length L Ch R = 1 ,2162    ,182.6,181.8,181.1
XS GIS Cut Line= 2
2384393.27337221657228.8118637972384548.37980747657389.045784525
#Sta/Elev= 30
       0 2974.97    16.5  2967.7    27.2 2962.25    39.1 2952.08      45 2948.61
    50.4 2947.66    56.2 2947.85    78.5 2946.12    81.5 2944.84    87.2 2941.27
    90.4 2939.74    92.8 2939.26   100.7 2938.78     107 2936.59   112.6 2937.35
  118.46 2935.57   124.9 2935.16   131.22935.581   135.3 2936.09   145.3  2938.5
   147.9 2939.56   153.7 2942.69   163.6 2948.82   182.5 2963.25   188.2 2966.76
   195.4 2969.64   200.3 2970.67     206 2973.35   214.5 2978.12     223 2981.57
#Mann= 4, -1 ,  0
       0    0.06       0     100     0.1       0  118.46   0.045       0
   131.2     0.1       0
Bank Sta=118.46,131.2
XS Rating Curve= 0 ,0
Exp/Cntr(USF)=0,0
Exp/Cntr=0.3,0.1

Type RM Length L Ch R = 1 ,1981    ,231.3,232.5,232.8
XS GIS Cut Line= 2
2384289.69956544657381.0105157332384441.18515206657514.805313744
#Sta/Elev= 30
       0 2959.76    27.4 2948.18    30.5 2946.55    41.5 2939.27    44.4 2937.94
    47.2  2937.1    67.3 2934.87    83.4 2933.69    86.9 2932.83    92.6 2930.93
    95.4 2930.44    98.2 2930.26   106.7 2930.96   115.1 2929.72   121.1 2927.74
   129.4 2927.96   136.7 2927.43   142.1 2927.16   147.4 2927.44   151.3 2928.84
   152.7 2929.79   157.7 2934.37   163.5 2938.91   174.7 2948.64   179.4 2952.33
   183.2 2954.87   187.6 2957.01   195.4 2959.08   199.7 2961.07   202.1 2962.48
#Mann= 4, -1 ,  0
       0    0.06       0      30     0.1       0   136.7   0.045       0
   147.4     0.1       0
Bank Sta=136.7,147.4
XS Rating Curve= 0 ,0
Exp/Cntr(USF)=0,0
Exp/Cntr=0.3,0.1

Type RM Length L Ch R = 1 ,1748    ,302.3,300.4,297.5
XS GIS Cut Line= 4
2384184.02038113657565.6718938172384243.90259168657619.751219679
2384286.23808395657672.6954653062384350.63621737657697.027995944
#Sta/Elev= 30
       0 2944.19     8.3 2940.12    16.4 2936.46    29.1 2929.94      41 2925.52
    47.9 2923.84    54.1 2920.44    59.2 2919.93    64.9 2919.94    67.7 2920.43
    73.4 2921.93    76.8 2922.26    87.6 2920.69   100.3 2918.28   108.1 2917.48
   110.4 2916.95  114.822915.095   118.9 2913.67   121.7 2914.07  124.432915.094
   128.6 2918.26   133.7 2921.55   138.9 2924.06     144 2927.12   154.8 2931.37
   162.8  2935.6   172.1 2940.03   184.8 2944.77   206.1 2955.52   217.3 2959.98
#Mann= 4, -1 ,  0
       0    0.06       0      30     0.1       0  114.82   0.045       0
  124.43     0.1       0
Bank Sta=114.82,124.43
XS Rating Curve= 0 ,0
Exp/Cntr(USF)=0,0
Exp/Cntr=0.3,0.1

Type RM Length L Ch R = 1 ,1448    ,132.3,135.3,137.3
XS GIS Cut Line= 3
2383996.96148376657787.8268812072384077.37391507657848.113765228
2384194.37183923657903.459977148
#Sta/Elev= 30
       0 2943.38     8.9 2937.16    17.5 2930.56    37.5  2917.8      54 2909.53
    60.4 2906.99      64 2905.92      69 2905.15    74.7  2903.7    82.3 2903.12
    91.8 2904.81     108 2904.54  128.022898.793   134.6 2897.77     139 2897.97
   140.92898.794   145.5 2901.44   148.5 2902.72   156.7 2903.55   165.6 2903.83
   169.5 2904.82   174.4 2907.67   178.8 2911.17   184.5 2914.11   192.1  2917.4
   196.5 2918.75   205.5 2922.84   218.7 2927.59   226.6 2929.84   229.9 2931.41
#Mann= 4, -1 ,  0
       0    0.06       0      10     0.1       0  128.02   0.045       0
   140.9     0.1       0
Bank Sta=128.02,140.9
XS Rating Curve= 0 ,0
Exp/Cntr(USF)=0,0
Exp/Cntr=0.3,0.1