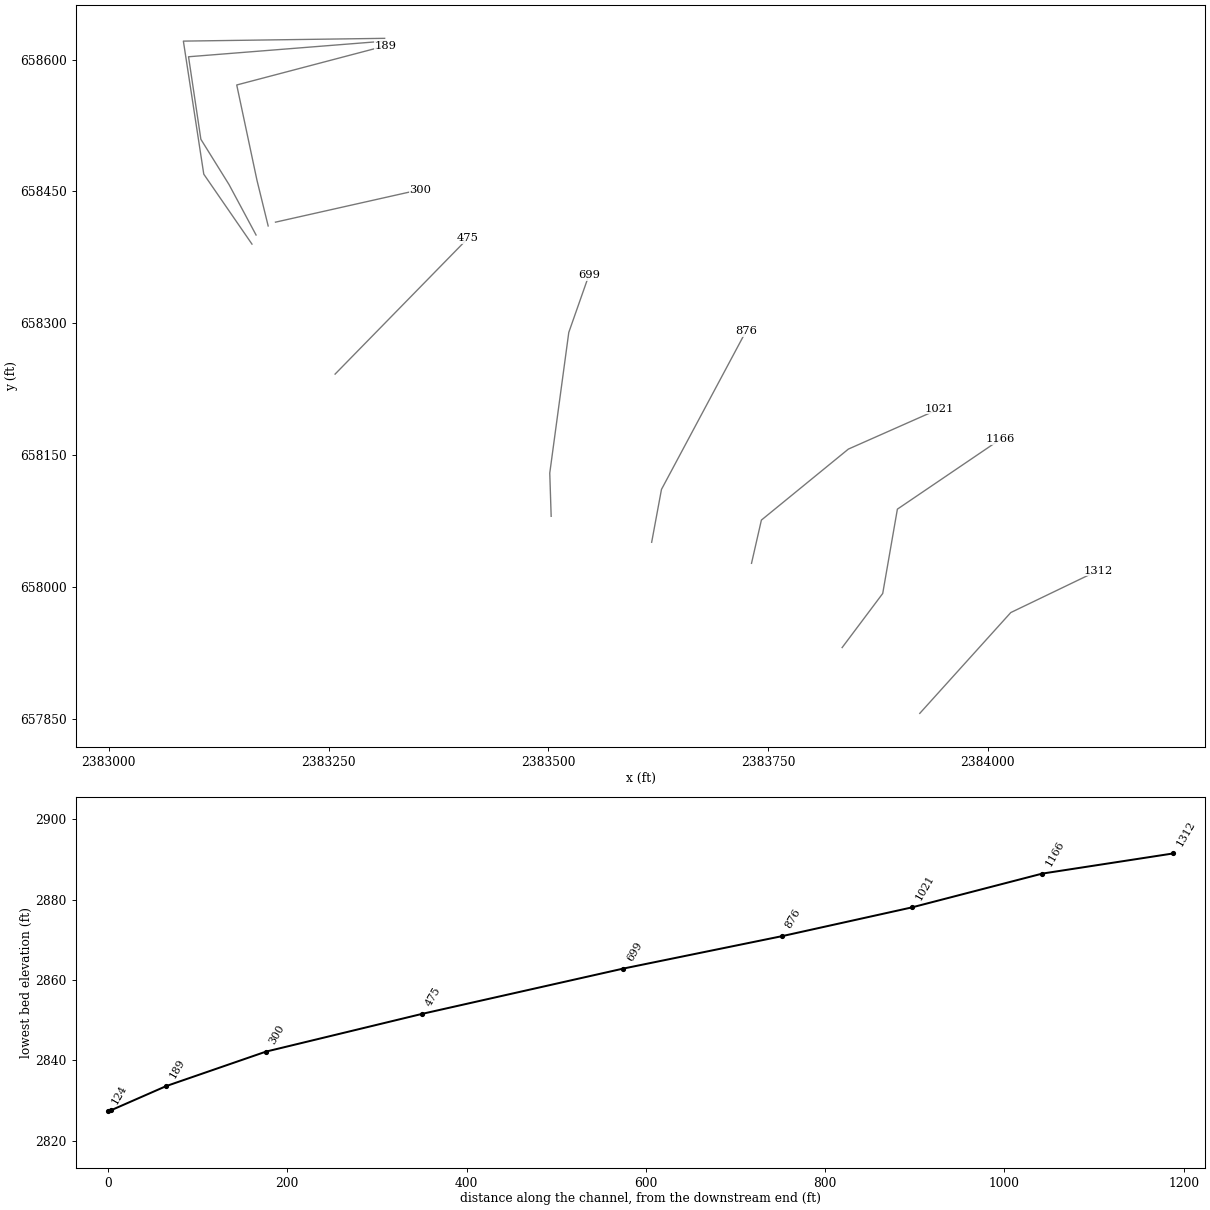
HEC-RAS study LOW2SPRRN.prj: LOW2SPRRN

--- LOW2SPRRN.g01 (geometry) --- (continued)

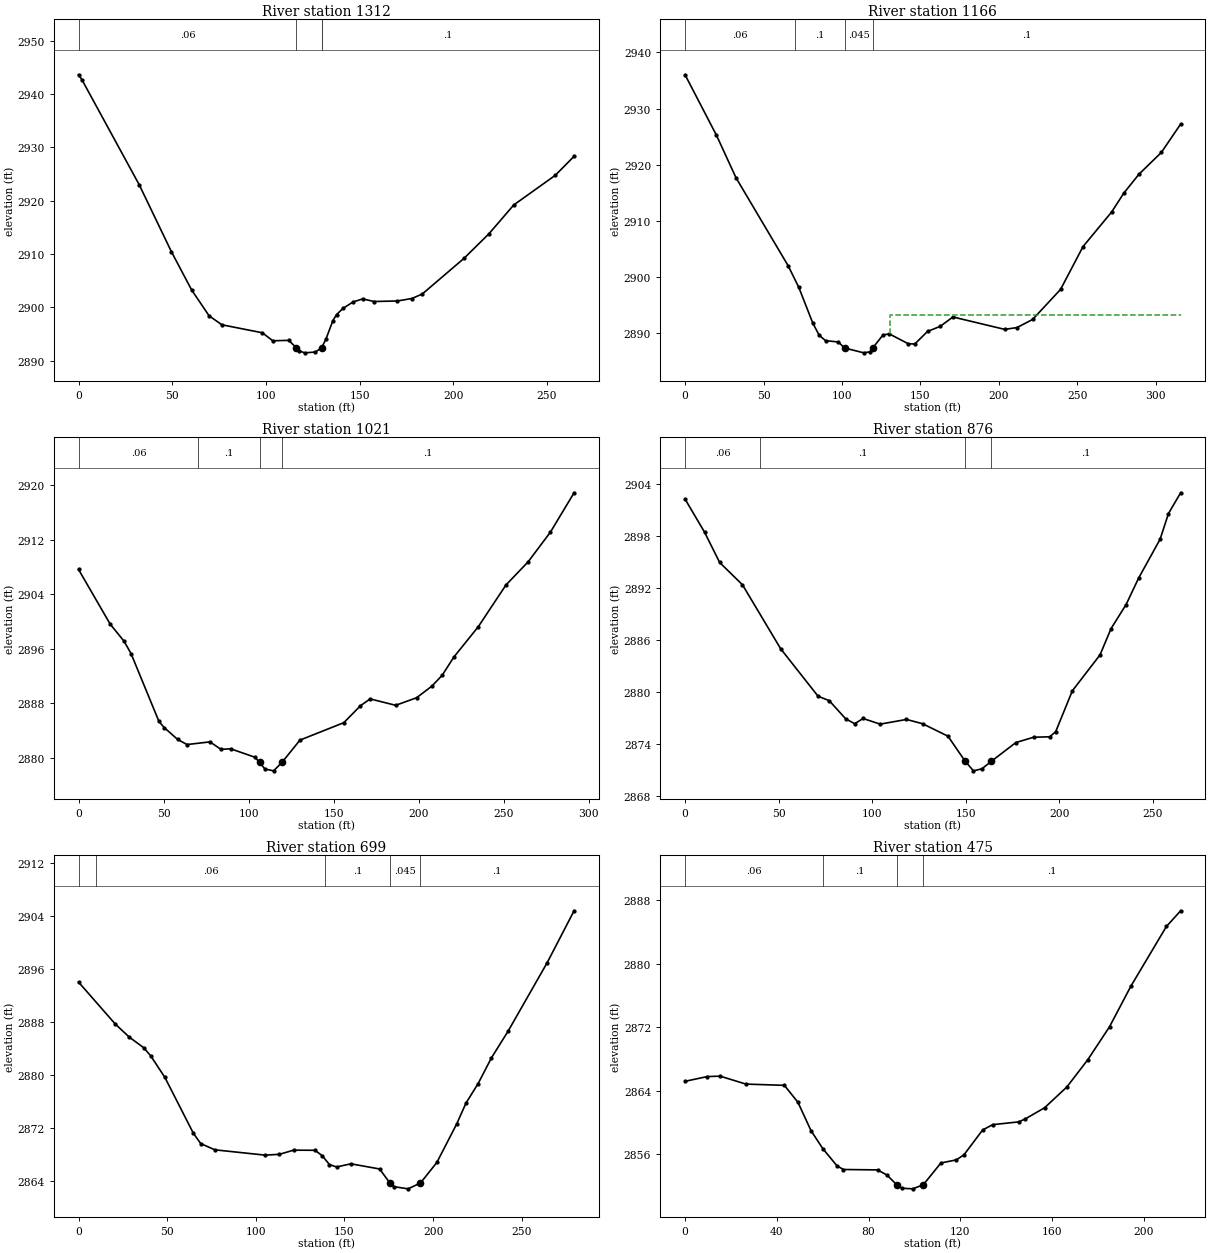
Type RM Length L Ch R = 1 ,1312    ,139.7,146.3,149.3
XS GIS Cut Line= 3
2383922.49619765657856.3688399082384026.00263999 657971.03166525
2384125.17048893658018.756192554
#Sta/Elev= 30
       0  2943.6     1.8 2942.69    32.4 2922.99    49.6 2910.43    60.4 2903.26
    69.7 2898.43    76.5 2896.75    98.1 2895.25   103.7 2893.75   112.2 2893.83
   116.32892.426   117.9 2891.85   120.7 2891.49   126.4 2891.64  129.712892.427
     132    2894   135.8 2897.55   137.7 2898.64   141.2 2899.84   146.6 2901.03
   151.7  2901.6   157.7 2901.11   170.2 2901.21   177.9 2901.67   183.5 2902.52
   205.7 2909.18     219 2913.78   232.3  2919.2   254.5 2924.77   264.5 2928.32
#Mann= 4, -1 ,  0
       0    0.06       0   116.3   0.045       0  129.71    0.06       0
     130     0.1       0
Bank Sta=116.3,129.71
XS Rating Curve= 0 ,0
Exp/Cntr(USF)=0,0
Exp/Cntr=0.3,0.1

Type RM Length L Ch R = 1 ,1166    ,152.8,145.5,140.5
XS GIS Cut Line= 4
2383834.19758637657931.2195736182383880.34986185657992.724632206
2383897.03935694658088.6447786672384014.20711508 658168.12620356
#Sta/Elev= 30
       0 2936.01      20 2925.24    32.5 2917.64    65.7 2901.98    72.5 2898.12
    81.4 2891.76    85.5 2889.59    89.5 2888.65    97.7  2888.4  101.622887.334
   113.9 2886.47     118 2886.66   119.62887.333   126.1 2889.65   130.1 2889.85
   142.3 2888.08   146.4 2888.05   154.5 2890.28   162.6 2891.19   170.7 2892.86
   203.7 2890.65   211.5 2890.97   221.5 2892.42   239.3 2897.78   253.6  2905.4
   271.9 2911.59   279.5 2914.89   289.2 2918.28   303.5 2922.17   315.8 2927.22
#Mann= 4, -1 ,  0
       0    0.06       0      70     0.1       0  101.62   0.045       0
   119.6     0.1       0
#XS Ineff= 2 , 0
                          130.58         2893.19
Permanent Ineff=
       F       F
Bank Sta=101.62,119.6
XS Rating Curve= 0 ,0
Exp/Cntr(USF)=0,0
Exp/Cntr=0.3,0.1

Type RM Length L Ch R = 1 ,1021    ,142.4,144.6,147.6
XS GIS Cut Line= 4
2383731.13021853658027.0486782782383742.35610656658076.205411615
2383841.30252133658156.9713820212383944.88506972658202.836367266
#Sta/Elev= 30
       0 2907.63    18.6 2899.61    26.8 2897.08    30.9 2895.27    47.3 2885.31
    50.4 2884.41    58.3 2882.67    63.8 2881.92    77.3 2882.31    83.8 2881.21
    89.4  2881.3   103.6 2880.07  106.472879.316   109.6 2878.33   114.7 2878.06
   119.72879.317   130.2 2882.57     156 2885.13   165.8 2887.62   171.5 2888.62
   186.5 2887.68   198.8 2888.79   207.8  2890.5   213.8 2892.07   220.7 2894.76
   235.1 2899.23   251.3 2905.33   264.4 2908.75   277.5 2913.11   291.4 2918.88
#Mann= 4, -1 ,  0
       0    0.06       0   70.42     0.1       0  106.47   0.045       0
   119.7     0.1       0
Bank Sta=106.47,119.7
XS Rating Curve= 0 ,0
Exp/Cntr(USF)=0,0
Exp/Cntr=0.3,0.1

Type RM Length L Ch R = 1 ,876     ,173.5,177,179.4
XS GIS Cut Line= 3
2383617.55506215658050.9857434612383628.71144515658111.106251884
2383724.78029882658290.847978096
#Sta/Elev= 30
       0 2902.22    10.4 2898.42    18.5 2894.92    30.7 2892.35    51.1 2884.99
    71.1 2879.52    77.1    2879    85.9 2876.91    90.7 2876.35    95.2 2876.95
   104.3  2876.3   118.4 2876.84     127 2876.35   140.6 2874.91  149.762872.033
   154.2 2870.92   158.7 2871.15  163.862872.032   176.9 2874.18   186.4 2874.79
     195 2874.84   198.2 2875.44   207.1 2880.14   221.9 2884.28   227.8 2887.31
   235.8 2890.06   242.6 2893.15     254 2897.59   258.5 2900.56     265 2902.95
#Mann= 4, -1 ,  0
       0    0.06       0      40     0.1       0  149.76   0.045       0
  163.86     0.1       0
Bank Sta=149.76,163.86
XS Rating Curve= 0 ,0
Exp/Cntr(USF)=0,0
Exp/Cntr=0.3,0.1

Type RM Length L Ch R = 1 ,699     ,226.1,224.5,218.3
XS GIS Cut Line= 4
2383503.25188912658080.5160058922383501.65263869658129.700223561
2383523.28813025658289.676602447 2383546.1252447658354.646952425
#Sta/Elev= 30
       0 2894.08    20.7 2887.75    28.7 2885.75    36.7 2884.18    40.7 2882.95
    48.7 2879.69    64.8 2871.24    68.9  2869.7    76.9 2868.75   105.2 2867.95
   113.3 2868.07   121.3  2868.7   133.4 2868.68   137.5 2867.85   141.5 2866.53
   145.6 2866.16   153.6 2866.64   169.8 2865.86  175.632863.746   177.8 2863.19
   185.9 2862.86  192.872863.745   202.1 2866.84   213.3 2872.66   218.6 2875.84
   225.4 2878.76   232.9 2882.64   242.3 2886.67   264.3 2896.99   279.5 2904.84
#Mann= 5, -1 ,  0
       0     0.1       0      10    0.06       0  139.21     0.1       0
  175.63   0.045       0  192.87     0.1       0
Bank Sta=175.63,192.87
XS Rating Curve= 0 ,0
Exp/Cntr(USF)=0,0
Exp/Cntr=0.3,0.1

Type RM Length L Ch R = 1 ,475     ,179.9,174.2,170.4
XS GIS Cut Line= 2
2383257.48251892658242.2582741362383408.53073671658396.678539092
#Sta/Elev= 30
       0 2865.16     9.7 2865.76    15.3 2865.81    26.5 2864.81    43.3 2864.65
    49.2 2862.51    54.9 2858.93      60 2856.68    66.2  2854.5      69 2854.03
    83.9 2853.98      88 2853.33   92.28  2852.1    94.5 2851.67    99.2 2851.59
  103.82  2852.1   111.5 2854.85   118.3 2855.25   121.6  2855.9   129.7 2859.02
   134.1 2859.69   145.4 2860.04   148.2  2860.4   156.7 2861.82   166.4 2864.44
   175.5 2867.87     185 2872.04   194.3 2877.16   209.8  2884.7     216 2886.68
#Mann= 4, -1 ,  0
       0    0.06       0      60     0.1       0   92.28   0.045       0
  103.82     0.1       0
Bank Sta=92.28,103.82
XS Rating Curve= 0 ,0
Exp/Cntr(USF)=0,0
Exp/Cntr=0.3,0.1

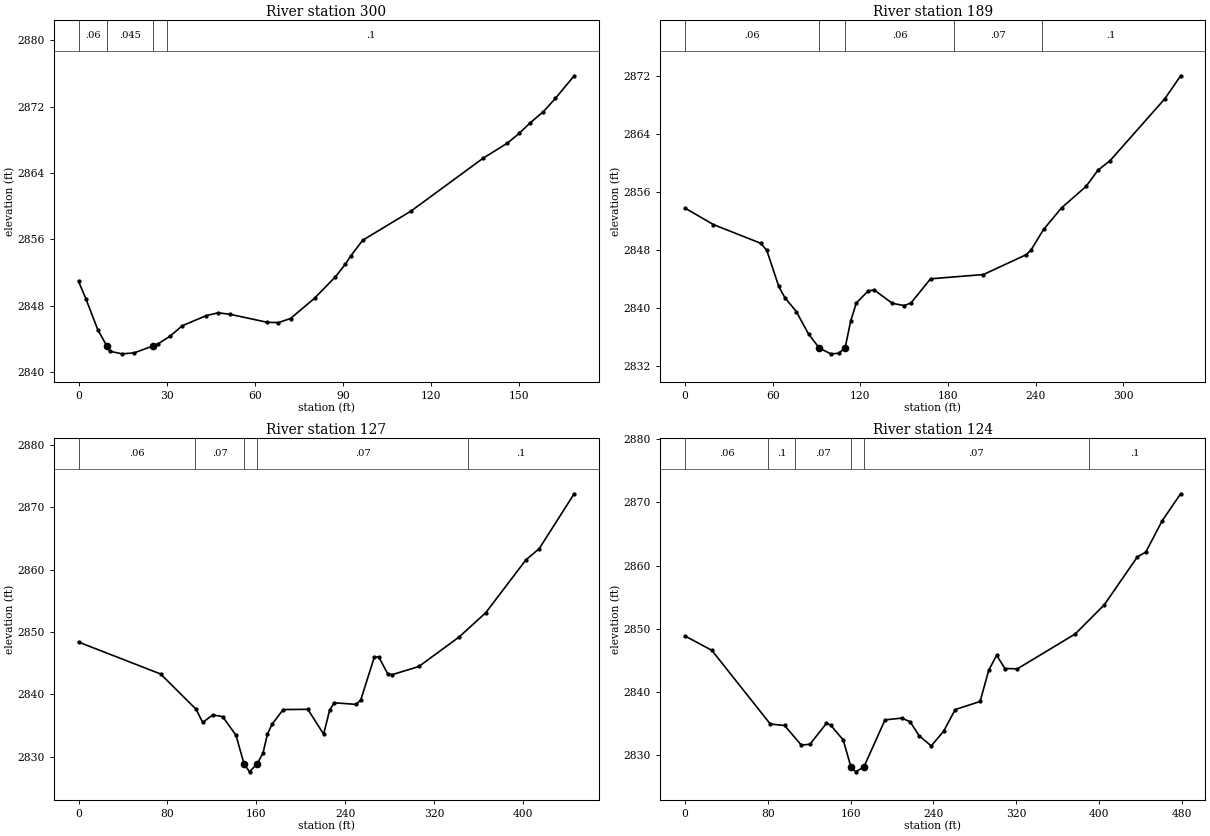
Type RM Length L Ch R = 1 ,300     ,94.1,111.3,116.4
XS GIS Cut Line= 2
2383189.69343096658415.0766388362383354.38674599658452.081803448
#Sta/Elev= 30
       0 2850.95     2.5 2848.85     6.6 2845.07    9.68 2843.13    10.7 2842.51
    14.8  2842.2    18.9 2842.31    25.22843.132    27.1 2843.41    31.2 2844.33
    35.3 2845.58    43.5 2846.81    47.6 2847.15    51.7 2846.96    64.3    2846
    68.1 2845.97    72.2 2846.46    80.4 2848.91    87.5 2851.49    90.9 2853.02
    92.7    2854    96.8  2855.9   113.2  2859.4   137.7 2865.76     146 2867.59
   150.1 2868.78   153.8 2870.04   158.3 2871.39   162.4 2872.99   168.8 2875.72
#Mann= 4, -1 ,  0
       0    0.06       0    9.68   0.045       0    25.2    0.06       0
      30     0.1       0
Bank Sta=9.68,25.2
XS Rating Curve= 0 ,0
Exp/Cntr(USF)=0,0
Exp/Cntr=0.3,0.1

Type RM Length L Ch R = 1 ,189     ,67.4,61.9,63.2
XS GIS Cut Line= 4
2383181.36590522658410.7695639272383168.67245822658462.531637333
2383145.60803085658571.1104255912383314.82397422658615.617768628
#Sta/Elev= 30
       0 2853.74    19.5 2851.46    51.9 2848.88      56  2847.9    64.2 2842.93
    68.3  2841.4    76.2 2839.47    84.6 2836.36      922834.413    99.8 2833.63
   105.1  2833.7   109.62834.438   113.4 2838.12   117.3 2840.66   125.5 2842.32
   129.6 2842.44   141.9  2840.6   150.1 2840.29   154.7 2840.65   168.1 2843.98
   204.3 2844.57   233.6 2847.31   236.9 2847.95   245.5  2850.8   257.9 2853.79
   274.5 2856.72   282.7 2858.96     291 2860.28   328.6 2868.85   339.3 2871.99
#Mann= 5, -1 ,  0
       0    0.06       0      92   0.045       0   109.6    0.06       0
   184.3    0.07       0   244.3     0.1       0
Bank Sta=92,109.6
XS Rating Curve= 0 ,0
Exp/Cntr(USF)=0,0
Exp/Cntr=0.3,0.1

Type RM Length L Ch R = 1 ,127     ,2.9,3.2,3.2
XS GIS Cut Line= 5
2383167.59239826658400.4799446562383136.77840955658457.949135734
2383104.82790643658509.3334500242383090.79051407658603.211383595
2383315.57051737658621.115504154
#Sta/Elev= 30
       0  2848.4    73.9 2843.28   105.7 2837.64   111.8 2835.51   120.8 2836.71
   129.7 2836.44   141.7 2833.46     1492828.845   153.9 2827.58   160.72828.853
     166 2830.56     170 2833.61   174.1 2835.19   184.2 2837.57   206.4 2837.61
   220.6 2833.63     226 2837.47   230.1 2838.66   250.1  2838.4   254.1 2839.15
   266.2 2845.97   270.2 2846.02   278.2 2843.34   282.2 2843.16   306.3 2844.48
   342.4 2849.19   366.5  2853.1   402.6 2861.57   414.6 2863.38   446.1 2872.19
#Mann= 5, -1 ,  0
       0    0.06       0  105.21    0.07       0     149   0.045       0
   160.7    0.07       0  350.64     0.1       0
Bank Sta=149,160.7
XS Rating Curve= 0 ,0
Exp/Cntr(USF)=0,0
Exp/Cntr=0.3,0.1

Type RM Length L Ch R = 1 ,124     ,,,
XS GIS Cut Line= 4
2383162.94508361658390.1119453922383108.12581513658469.664461658
2383084.92373216658621.0042400892383313.85747653658624.161704478
#Sta/Elev= 30
       0 2848.86      26 2846.58    82.4 2834.93    96.2  2834.7   112.3 2831.61
   120.7 2831.73   136.6 2835.04   140.6 2834.77   152.8 2832.42   160.3 2828.13
   164.9 2827.37   172.82828.145   193.2 2835.59   209.4 2835.87   217.5 2835.29
     226  2833.1   237.8 2831.47   249.7 2833.77     261 2837.22     285  2838.5
   293.4 2843.45     301 2845.81     309 2843.71     321 2843.66     377 2849.19
     405  2853.8     437 2861.39     445 2862.12     461 2867.11   478.7 2871.35
#Mann= 6, -1 ,  0
       0    0.06       0      80     0.1       0  106.61    0.07       0
   160.3   0.045       0   172.8    0.07       0  389.72     0.1       0
Bank Sta=160.3,172.8
XS Rating Curve= 0 ,0
Exp/Cntr(USF)=0,0
Exp/Cntr=0.3,0.1
LCMann Table=0

Chan Stop Cuts=-1
Use User Specified Reach Order=0
Composite Channel Slope=5